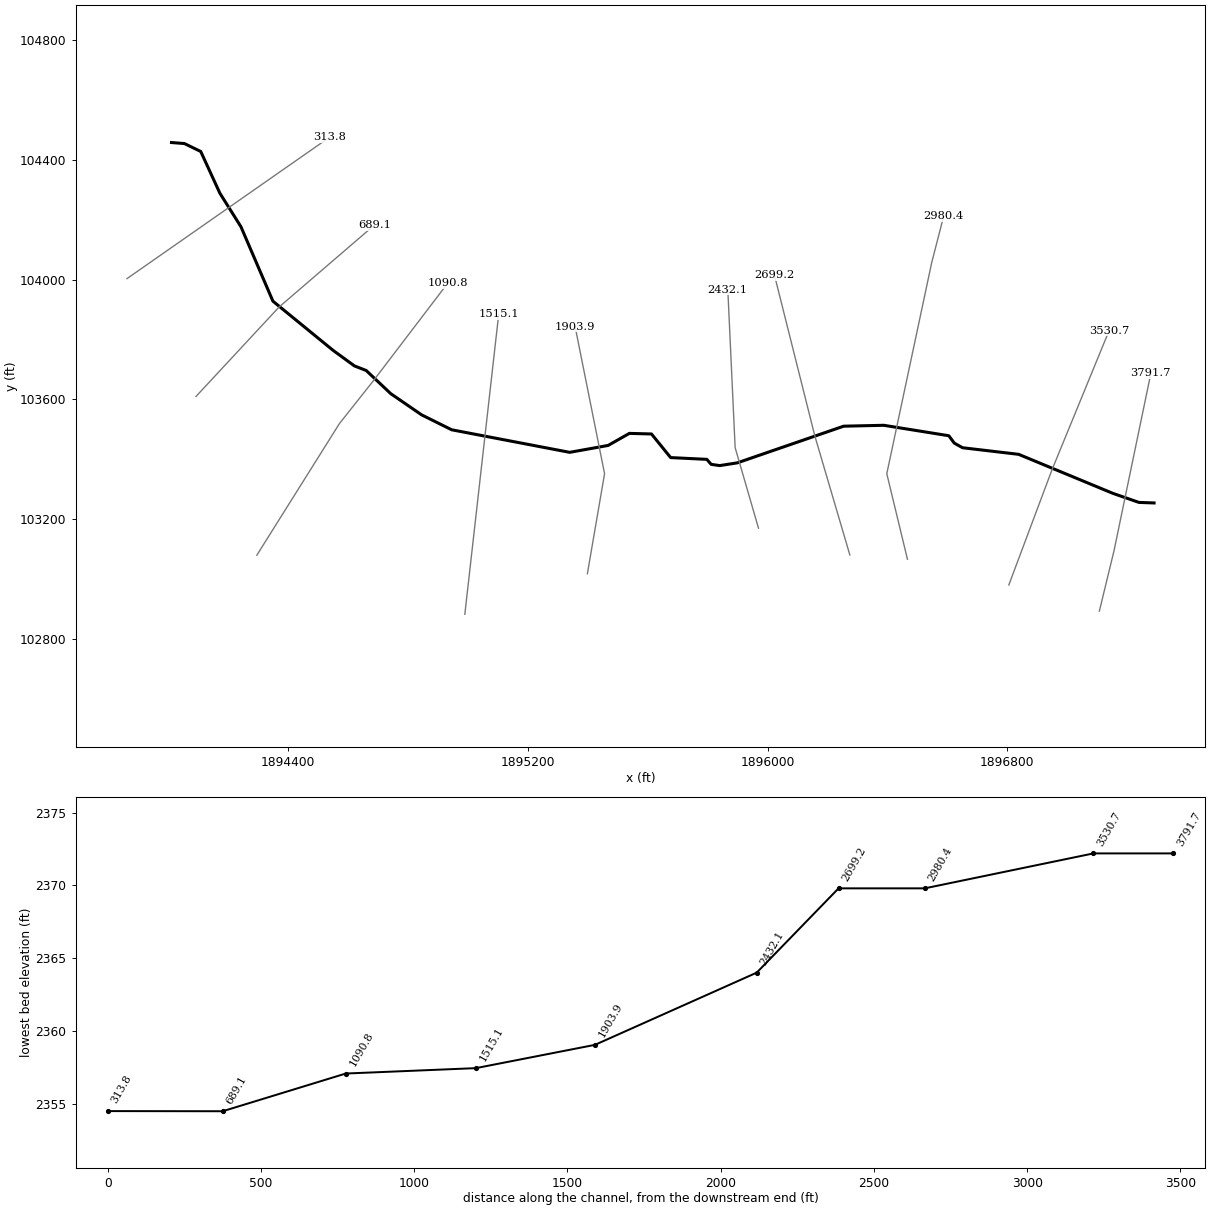
--- PrdHllw.prj (project) ---

Proj Title=PrdHllw
Current Plan=p01
Default Exp/Contr=0,0
English Units
Geom File=g01
Flow File=f01
Plan File=p01
BEGIN DESCRIPTION:
END DESCRIPTION:
DSS Export Rating Curves= 0
DSS Export Rating Curve Sorted= 0
DSS Export Volume Flow Curves= 0
DXF OffsetX= 0
DXF OffsetY= 0
DXF ScaleX= 0
DXF ScaleY= 0

--- PrdHllw.p01 (plan) ---

Plan Title=Floodplain
Program Version=4.00
Geom File=g01
Flow File=f01
K Sum by GR=0
Std Step Tol=0.01
Critical Tol=0.01
Num of Std Step Trials=20
Max Error Tol=0.3
Flow Tol Ratio=0.001
Split Flow NTrial=30
Split Flow Tol=0.02
Split Flow Ratio=0.02
Log Output Level=0
Friction Slope Method=1
Unsteady Friction Slope Method=2
Unsteady Bridges Friction Slope Method=1
Global Log Level=0
CheckData=False
Run HTab=0
Run UNet=0
Run PostProcess=0
UNET Theta=0
UNET Theta Warmup=0
UNET ZTol=0
UNET ZSATol=0
UNET MxIter=0
UNET MaxInSteps=0
UNET DtIC=0
UNET DtMin=0
UNET MaxCRTS=0
UNET WFStab=0
UNET SFStab=0
UNET WFX=0
UNET SFX=0
UNET DSS MLevel=0
UNET DZMax Abort=0
UNET Convert EG Bridges=0
UNET Use Existing IB Tables=0
UNET Froude Limit=0
UNET Froude Power=0
Write IC File=0
Echo Input=False
Echo Output=False
Write Detailed=0

--- PrdHllw.f01 (steady flow) ---

Flow Title=NFF Regression Equation
Program Version=4.00
Number of Profiles=1
Profile Names=P100yr
River Rch & RM=PrdHllw,Main      ,3791.7
504.6588
River Rch & RM=PrdHllw,Main      ,2980.4
539.7373
River Rch & RM=PrdHllw,Main      ,1515.1
590.3180
River Rch & RM=PrdHllw,Main      ,689.1
655.4782
River Rch & RM=PrdHllw,Main      ,313.8
665.2071
Boundary for River Rch & Prof#=PrdHllw,Main      ,1
Up Type=0
Dn Type=3
Dn Slope=0.002433

--- PrdHllw.g01 (geometry) ---

Geom Title=USGS 3m DEM
Program Version=4.10

River Reach=PrdHllw         ,Main
Reach XY= 30
     1897289.945       103254.22     1897239.509      103256.015
     1897152.167      103286.426     1896837.931      103416.635
     1896650.707      103438.684     1896622.936      103454.205
     1896604.844      103478.758     1896387.749      103513.648
      1896253.78      103510.668     1895898.734      103388.185
     1895839.955      103379.042     1895811.473      103383.153
     1895796.979      103399.877     1895676.301      103405.764
     1895612.282      103484.663     1895538.371      103486.625
     1895467.534      103446.344     1895339.234      103423.313
     1894945.307      103498.669     1894844.906      103548.557
     1894742.121      103619.198     1894659.949      103696.719
     1894620.626      103712.048     1894549.145      103764.205
     1894348.624      103928.267     1894241.853      104176.965
     1894171.541      104288.944     1894107.651      104428.341
     1894053.208      104454.829     1894010.103      104458.232

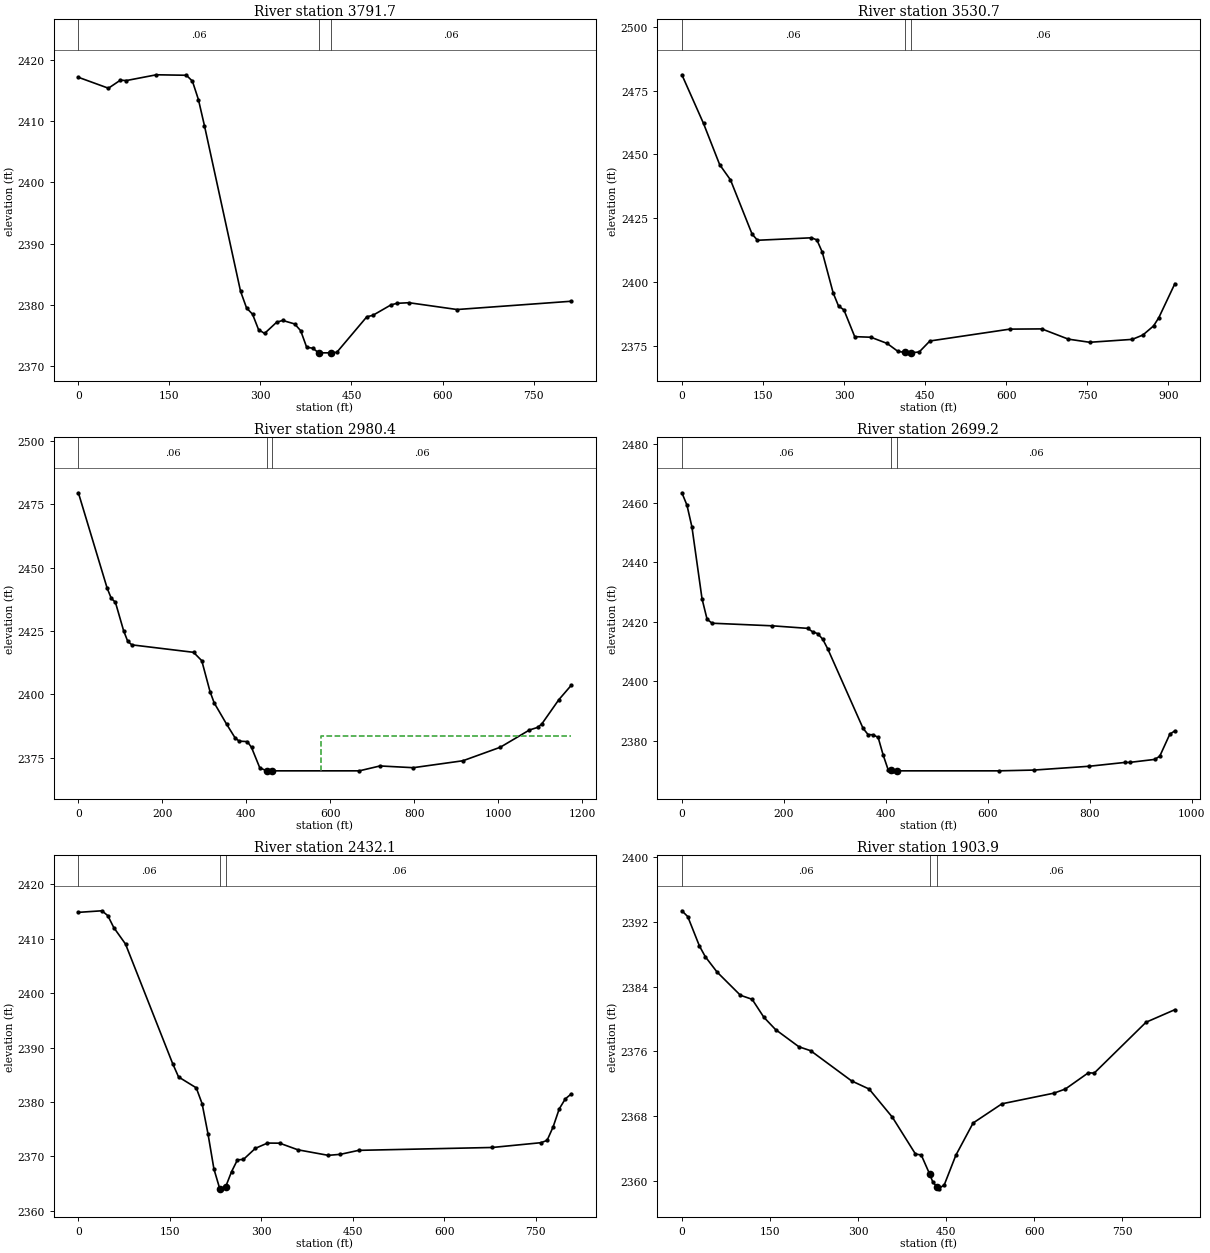
Type RM Length L Ch R = 1 ,3791.7  ,264.4,261,257.1
XS GIS Cut Line= 3
     1897107.385      102893.068     1897156.325      103094.944
     1897279.197      103686.941
#Sta/Elev= 30
       0 2417.11    49.5 2415.33    69.2 2416.64    79.1 2416.58   128.6 2417.52
     178 2417.44   187.9 2416.48   197.8 2413.48   207.7 2409.24   267.2 2382.24
   277.1 2379.52     287 2378.49   296.9 2375.98   306.8 2375.36   326.7 2377.19
   336.6 2377.48   356.4 2376.91   366.3 2375.81   376.2  2373.1   386.1 2372.96
     396  2372.2   415.9  2372.2   425.8 2372.28   475.3 2378.08   485.2 2378.31
     515 2380.01   524.9 2380.27   544.7 2380.37     624 2379.26   812.3 2380.61
#Mann= 3 , 0 , 0
       0     .06       0     396    .045       0   415.9     .06       0
#XS Ineff= 2 , 0
          337.48 2377.39
Permanent Ineff=
       F       F
Bank Sta=396,415.9
XS Rating Curve= 0 ,0
Exp/Cntr=0.3,0.1

Type RM Length L Ch R = 1 ,3530.7  ,546.5,550.4,554.7
XS GIS Cut Line= 3
     1896805.216      102980.397     1896948.838       103364.07
     1897139.502      103829.036
#Sta/Elev= 30
       0 2481.25      40 2462.16    69.9    2446    89.9 2440.03   129.9 2418.76
   139.9 2416.35   239.8 2417.32   249.8 2416.49   259.8 2411.66   279.8 2395.79
   289.8 2390.57   299.8 2389.05   319.8 2378.55   349.7 2378.32   379.7  2375.9
   399.7 2372.78   412.3 2372.38   419.5  2372.2   424.3  2372.2   439.2 2372.56
   458.9 2376.85   606.8  2381.5   665.9 2381.59   715.1 2377.57   754.6 2376.34
   833.4 2377.48   853.1  2379.2   872.8 2382.76   882.6 2386.03   912.2 2399.32
#Mann= 3 , 0 , 0
       0     .06       0   412.3    .045       0   424.3     .06       0
Bank Sta=412.3,424.3
XS Rating Curve= 0 ,0
Exp/Cntr=0.3,0.1

Type RM Length L Ch R = 1 ,2980.4  ,270.4,281.1,291
XS GIS Cut Line= 4
     1896466.722      103066.188     1896397.763      103351.876
      1896547.64       104056.91     1896587.404      104211.375
#Sta/Elev= 30
       0 2479.62    68.6 2441.91    78.4 2437.91    88.2 2436.38   107.8 2425.11
   117.6 2420.94   127.4 2419.56   274.3 2416.61   293.9  2413.3   313.6 2401.09
   323.5 2396.63   353.1 2388.22   372.9 2382.91   382.8 2381.54   402.5 2381.34
   412.4 2379.04   432.1 2370.98   448.3 2369.83   451.9  2369.8   460.3  2369.8
   669.1  2369.8   718.5 2371.73   797.5 2371.04   915.9 2373.78  1004.8 2379.11
  1074.5 2385.94  1094.4 2386.98  1104.4 2388.45  1144.3 2397.88  1174.2 2403.63
#Mann= 3 , 0 , 0
       0     .06       0   448.3    .045       0   460.3     .06       0
#XS Ineff= 2 , 0
                           578.8         2383.62
Permanent Ineff=
       F       F
Bank Sta=448.3,460.3
XS Rating Curve= 0 ,0
Exp/Cntr=0.3,0.1

Type RM Length L Ch R = 1 ,2699.2  ,267.1,267,267.8
XS GIS Cut Line= 3
     1896274.448      103080.445     1896157.515      103478.191
      1896023.07      104014.088
#Sta/Elev= 30
       0 2463.45     9.9  2459.3    19.7 2451.94    39.5 2427.76    49.4 2420.86
    59.2 2419.52   177.7 2418.64   246.8 2417.79   256.6 2416.61   266.5 2416.01
   276.4  2414.1   286.3 2410.82   355.4 2384.12   365.2 2382.02   375.1 2381.94
     385 2381.07   394.8 2375.16   404.7 2370.14   409.6 2369.97   414.6  2369.8
   421.6  2369.8   621.8  2369.8   690.8 2370.06   799.4 2371.35   868.4 2372.62
   878.3 2372.64   927.6 2373.65   937.5 2374.74   957.2 2382.15   967.1 2383.27
#Mann= 3 , 0 , 0
       0     .06       0   409.6    .045       0   421.6     .06       0
Bank Sta=409.6,421.6
XS Rating Curve= 0 ,0
Exp/Cntr=0.3,0.1

Type RM Length L Ch R = 1 ,2432.1  ,528.4,527.7,526.7
XS GIS Cut Line= 3
     1895969.543      103169.882     1895891.546      103439.049
     1895867.076      103966.678
#Sta/Elev= 30
       0 2414.87    38.6 2415.16    48.3 2414.26      58 2412.08    77.3 2409.04
   154.6 2387.05   164.3 2384.59   193.3 2382.59   202.9 2379.67   212.6  2374.1
   222.3 2367.65   231.9 2364.01   241.6 2364.41   251.2 2367.17   260.9 2369.35
   270.6 2369.41   290.2 2371.46   310.1 2372.43   330.1 2372.41     360 2371.19
   409.8 2370.17   429.7 2370.36   459.6 2371.09   678.9 2371.62   758.6  2372.5
   768.6 2372.92   778.5  2375.4   788.5 2378.71   798.5 2380.56   808.4 2381.48
#Mann= 3 , 0 , 0
       0     .06       0   231.9    .045       0   241.6     .06       0
Bank Sta=231.9,241.6
XS Rating Curve= 0 ,0
Exp/Cntr=0.3,0.1

Type RM Length L Ch R = 1 ,1903.9  ,395.1,388.6,382
XS GIS Cut Line= 3
     1895398.308      103017.988     1895455.678      103351.876
     1895357.482      103842.623
#Sta/Elev= 30
       0 2393.35      10 2392.63    29.9    2389    39.9 2387.68    59.8  2385.8
    99.6 2382.93   119.6 2382.43   139.5 2380.22   159.4  2378.7   199.3 2376.57
   219.2 2376.09     289 2372.36   318.8 2371.36   358.4 2367.88   397.7 2363.34
   407.5 2363.23   421.9 2360.86   427.1 2359.91   433.9 2359.31   436.9 2359.05
   446.7 2359.54   466.4 2363.19   495.8 2367.17   544.9 2369.54   633.2 2370.85
   652.8 2371.36   692.1 2373.37   701.9 2373.32   790.2  2379.6   839.3 2381.15
#Mann= 3 , 0 , 0
       0     .06       0   421.9    .045       0   433.9     .06       0
Bank Sta=421.9,433.9
XS Rating Curve= 0 ,0
Exp/Cntr=0.3,0.1

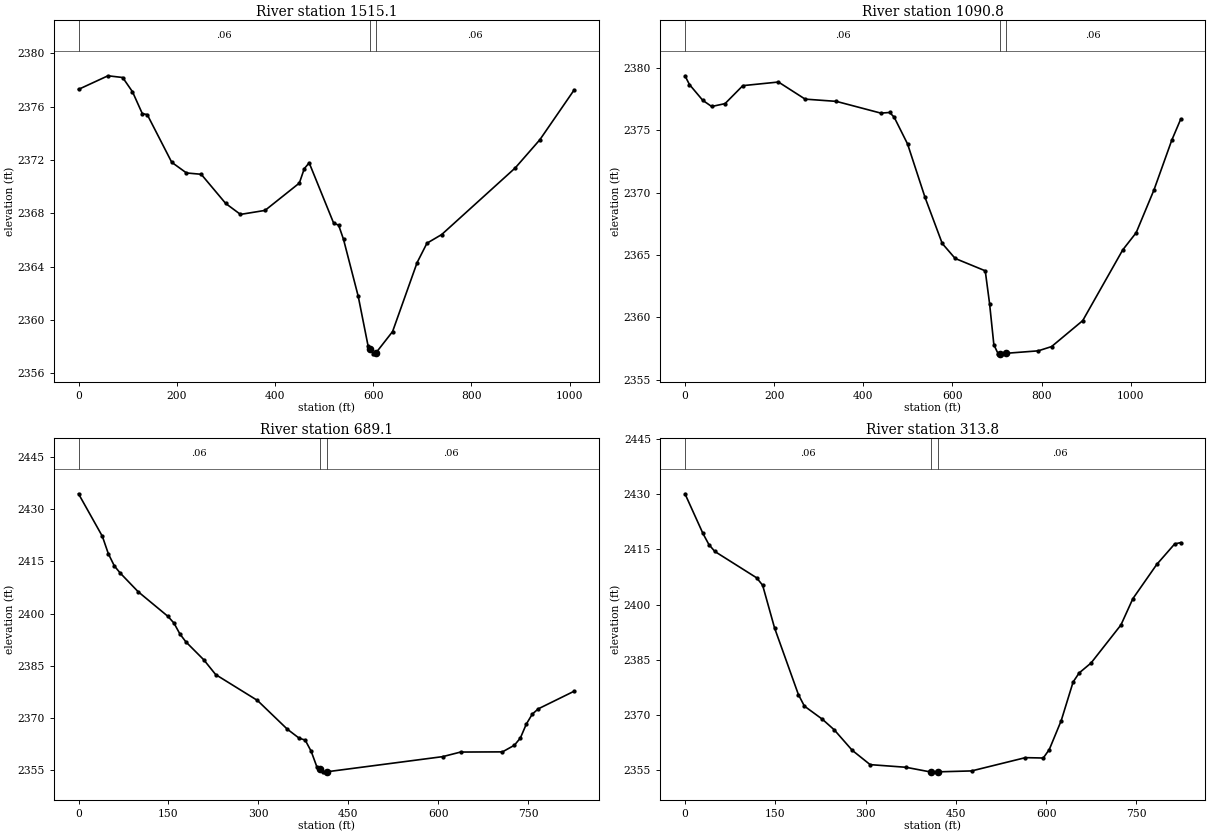
Type RM Length L Ch R = 1 ,1515.1  ,435.9,424.3,412.9
XS GIS Cut Line= 2
     1894989.224      102882.363     1895102.357      103885.128
#Sta/Elev= 30
       0 2377.29      60 2378.31    89.9 2378.18   109.9 2377.11   129.9 2375.47
   139.9  2375.4   189.8 2371.82   219.8 2371.02   249.8 2370.92   299.7 2368.73
   329.7 2367.91   379.7 2368.21   449.6 2370.26   459.6 2371.34   469.6 2371.78
   519.6 2367.24   529.5 2367.11   539.5 2366.04   569.5 2361.76   589.5 2358.05
   593.7  2357.8   599.5 2357.45   605.7 2357.53   639.4 2359.12   689.4  2364.3
   709.4 2365.75   739.4  2366.4   889.2  2371.4   939.2 2373.51  1009.1 2377.25
#Mann= 3 , 0 , 0
       0     .06       0   593.7    .045       0   605.7     .06       0
Bank Sta=593.7,605.7
XS Rating Curve= 0 ,0
Exp/Cntr=0.3,0.1

Type RM Length L Ch R = 1 ,1090.8  ,403.5,401.6,397.2
XS GIS Cut Line= 4
     1894294.895       103079.65      1894570.79      103519.622
     1894684.679      103663.291     1894932.698      103989.118
#Sta/Elev= 30
       0 2379.35      10 2378.65      40 2377.38    59.9 2376.89    89.9 2377.12
   129.8 2378.56   209.7 2378.85   269.6 2377.48   339.6  2377.3   439.4 2376.36
   459.4 2376.41   469.4 2376.03   499.4 2373.89   538.6 2369.61   577.2 2365.92
   606.2 2364.72   673.7 2363.73   683.4 2361.11     693 2357.82   702.6 2357.08
   707.3 2357.09   719.3 2357.12   792.5 2357.32   822.5 2357.66   892.4 2359.74
   982.3 2365.41  1012.3 2366.78  1052.2  2370.2  1092.2 2374.19  1112.1 2375.86
#Mann= 3 , 0 , 0
       0     .06       0   707.3    .045       0   719.3     .06       0
Bank Sta=707.3,719.3
XS Rating Curve= 0 ,0
Exp/Cntr=0.3,0.1

Type RM Length L Ch R = 1 ,689.1   ,379.8,375.3,373.2
XS GIS Cut Line= 3
     1894091.888      103610.066     1894369.425      103908.952
     1894686.872      104182.008
#Sta/Elev= 30
       0 2434.45    39.8 2422.21    49.7 2417.23    59.7 2413.72    69.6 2411.64
    99.5 2406.28   149.2 2399.19   159.2 2397.26   169.1 2394.14   179.1 2391.86
   208.9 2386.71   228.8 2382.45   298.4 2375.02   348.2 2366.76   368.1 2364.15
     378 2363.63     388  2360.4   397.9 2355.74   401.9 2355.24   407.9 2354.49
   413.9  2354.5   607.3 2358.86   637.2 2360.18     707 2360.23   726.9 2362.14
   736.9 2364.22   746.8 2368.22   756.8  2371.1   766.8 2372.61   826.6 2377.68
#Mann= 3 , 0 , 0
       0     .06       0   401.9    .045       0   413.9     .06       0
Bank Sta=401.9,413.9
XS Rating Curve= 0 ,0
Exp/Cntr=0.3,0.1

Type RM Length L Ch R = 1 ,313.8   ,294.8,313.8,332.8
XS GIS Cut Line= 2
     1893861.572      104003.704     1894536.611      104475.251
#Sta/Elev= 30
       0 2430.12    29.8 2419.34    39.7 2416.32    49.6 2414.43     119 2407.27
     129 2405.25   148.8 2393.64   188.5 2375.48   198.4 2372.37   228.2 2368.81
     248 2365.92   277.8 2360.36   307.6 2356.46   367.1 2355.74   406.8  2354.5
   408.7  2354.5   420.7  2354.5   476.2 2354.75   565.5 2358.36   595.2 2358.26
   605.2 2360.57     625 2368.42   644.8 2378.94   654.8 2381.39   674.6  2384.1
   724.2 2394.44   744.1 2401.61   783.7  2410.9   813.5 2416.48   823.4 2416.84
#Mann= 3 , 0 , 0
       0     .06       0   408.7    .045       0   420.7     .06       0
Bank Sta=408.7,420.7
XS Rating Curve= 0 ,0
Exp/Cntr=0.3,0.1

Chan Stop Cuts=-1
Use User Specified Reach Order=0
Composite Channel Slope=5